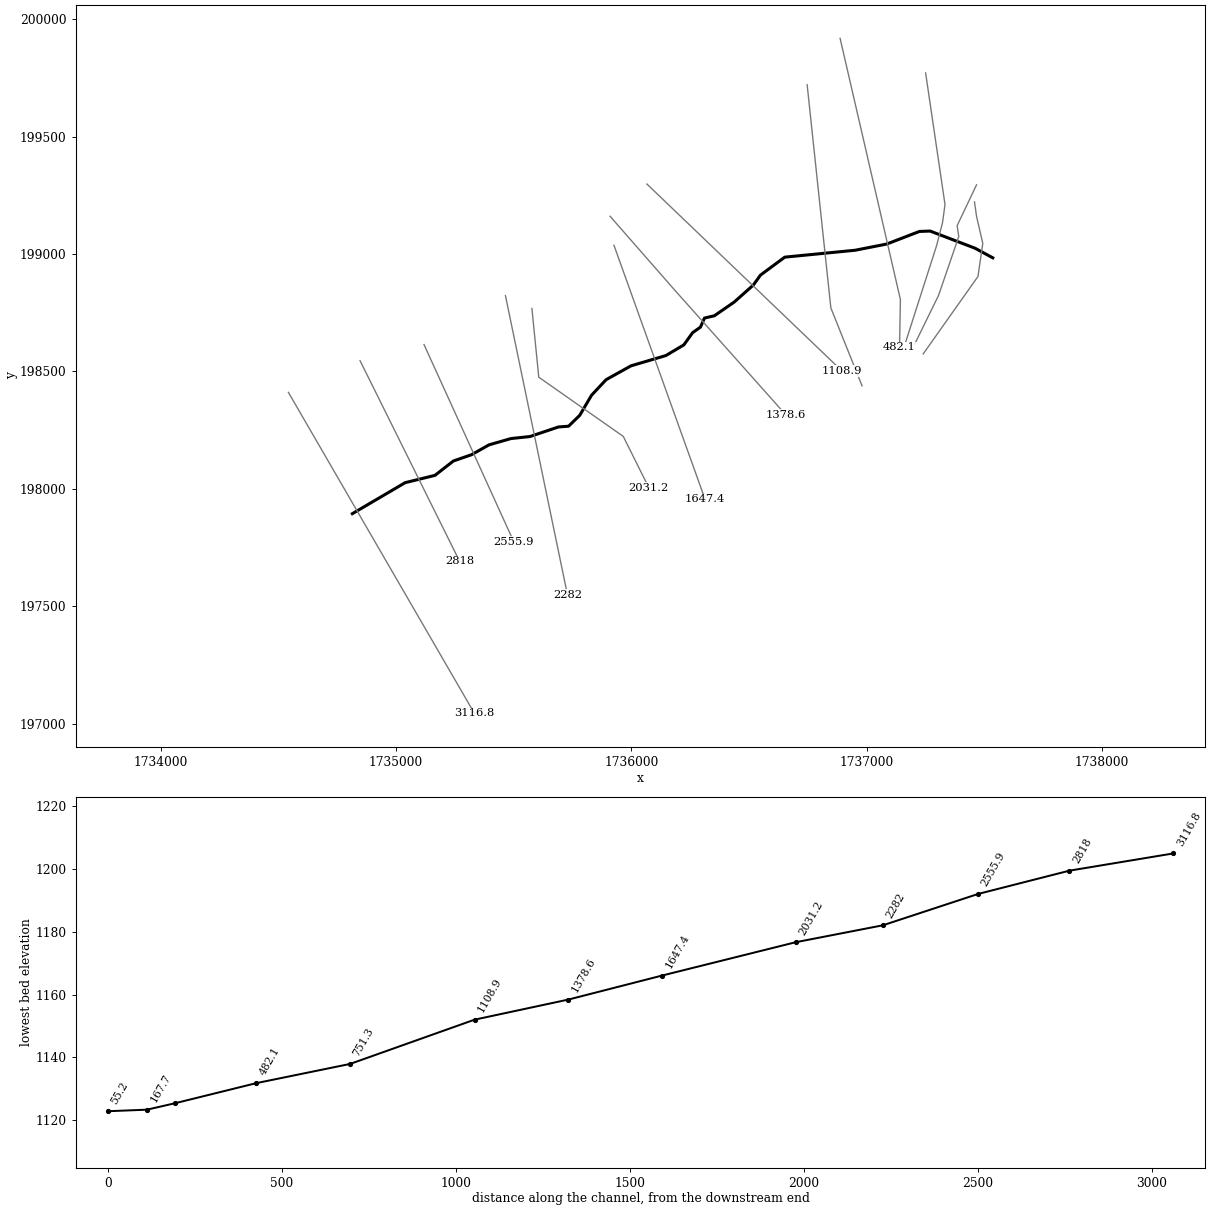
--- RtFkMzleCr.prj (project) ---

Proj Title=RtFkMzleCr
Current Plan=p01
Geom File=g01
Flow File=f01
Plan File=p01
DSS Export Rating Curves=0
DSS Export Rating Curve Sorted=0
DSS Export Volume Flow Curves=0
DXF OffsetX=0
DXF OffsetY=0
DXF ScaleX=0
DXF ScaleY=0

--- RtFkMzleCr.p01 (plan) ---

Plan Title=Floodplain
Program Version=4.00
Geom File=g01
Flow File=f01
K Sum by GR=0
Std Step Tol=0.01
Critical Tol=0.01
Num of Std Step Trials=20
Max Error Tol=0.3
Flow Tol Ratio=0.001
Split Flow NTrial=30
Split Flow Tol=0.02
Split Flow Ratio=0.02
Log Output Level=0
Friction Slope Method=1
Unsteady Friction Slope Method=2
Unsteady Bridges Friction Slope Method=1
Global Log Level=0
CheckData=False
Run HTab=0
Run UNet=0
Run PostProcess=0
UNET Theta=0
UNET Theta Warmup=0
UNET ZTol=0
UNET ZSATol=0
UNET MxIter=0
UNET MaxInSteps=0
UNET DtIC=0
UNET DtMin=0
UNET MaxCRTS=0
UNET WFStab=0
UNET SFStab=0
UNET WFX=0
UNET SFX=0
UNET DSS MLevel=0
UNET DZMax Abort=0
UNET Convert EG Bridges=0
UNET Use Existing IB Tables=0
UNET Froude Limit=0
UNET Froude Power=0
Write IC File=0
Echo Input=False
Echo Output=False
Write Detailed=0

--- RtFkMzleCr.f01 (steady flow) ---

Flow Title=NFF Regression Equation
Program Version=4.00
Number of Profiles=1
Profile Names=P100yr
River Rch & RM=RtFkMzleCr,Main      ,3116.8
600.4487
River Rch & RM=RtFkMzleCr,Main      ,2031.2
634.9530
River Rch & RM=RtFkMzleCr,Main      ,248.7
688.6546
Boundary for River Rch & Prof#=RtFkMzleCr,Main      ,1
Up Type=0
Dn Type=3
Dn Slope=0.017768

--- RtFkMzleCr.g01 (geometry) ---

Geom Title=USGS 10m DEM
Program Version=4.00

River Reach=RtFkMzleCr     ,Main
Reach XY= 30
     1734814.373      197893.870     1735038.773      198025.933
     1735165.468      198057.070     1735243.846      198118.270
     1735321.152      198145.112     1735395.236      198186.986
     1735488.646      198213.828     1735569.173      198222.417
     1735690.498      198263.217     1735733.446      198266.438
     1735780.688      198312.607     1735831.151      198398.501
     1735892.856      198464.515     1735998.995      198523.660
     1736146.917      198567.320     1736223.270      198612.713
     1736260.624      198664.775     1736293.908      198688.396
     1736311.087      198727.048     1736352.828      198736.711
     1736436.897      198794.742     1736518.549      198867.424
     1736549.097      198910.085     1736652.326      198986.453
     1736952.005      199015.947     1737085.930      199042.365
     1737224.824      199096.002     1737270.119      199097.582
     1737461.303      199024.374     1737536.438      198983.623

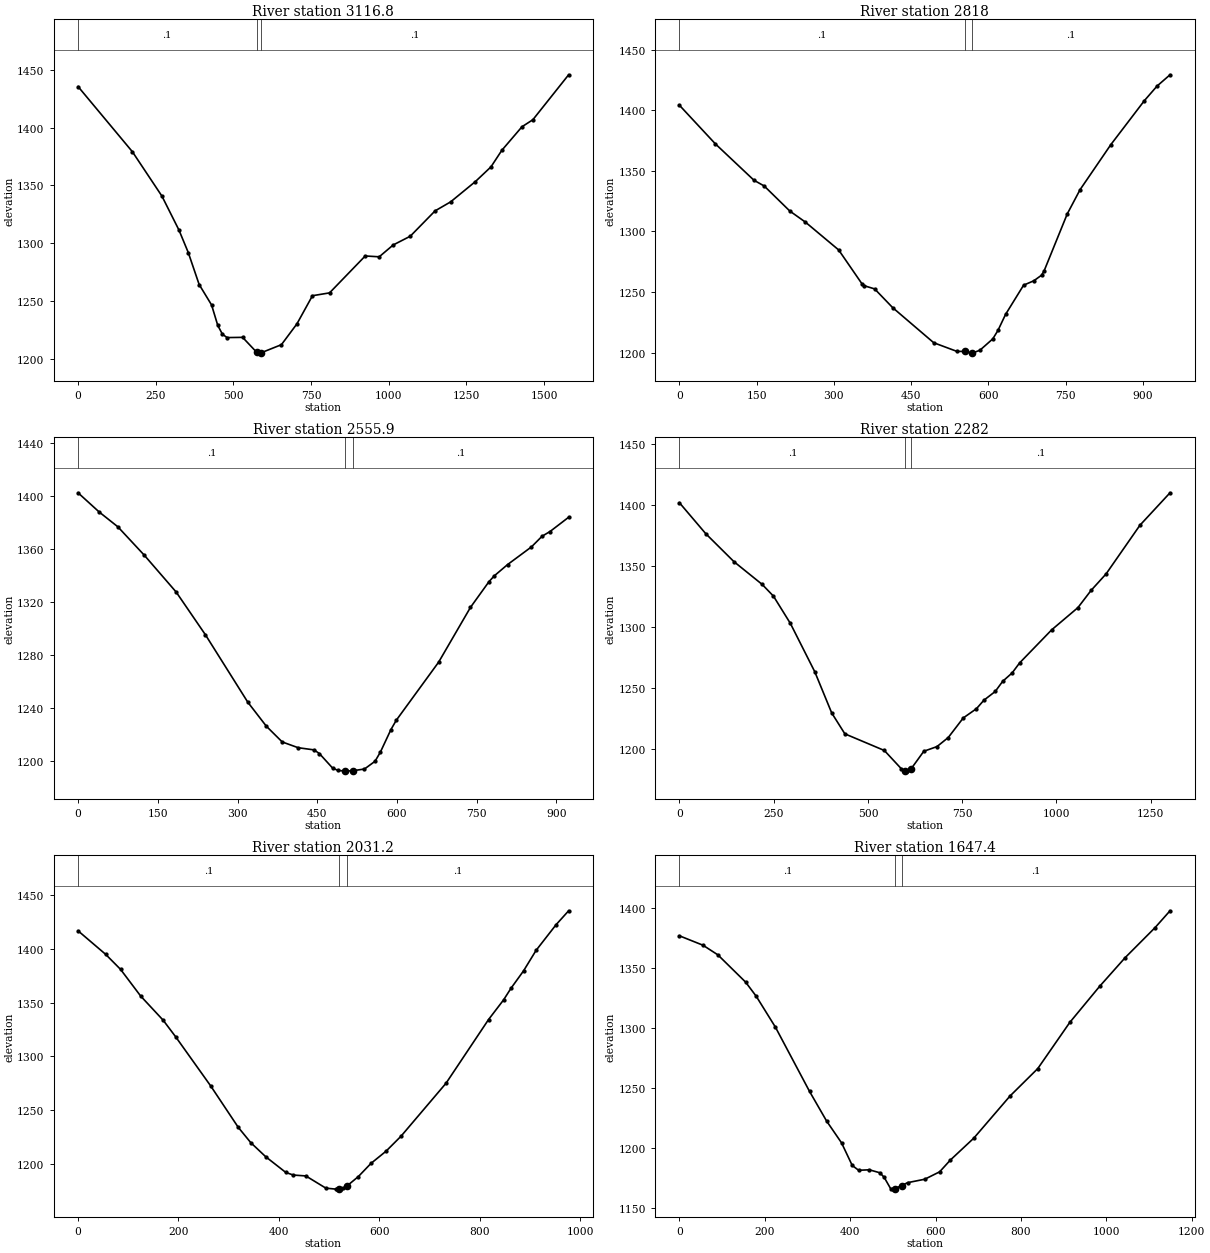
Type RM Length L Ch R = 1 ,3116.8,300,298.7,297.4
XS GIS Cut Line= 2
     1734542.686      198410.408     1735333.229      197043.357
#Sta/Elev= 30
       0 1435.44   174.9 1379.09   269.9 1340.78   324.8 1311.40   354.8 1291.95
   389.8 1264.33   429.8 1246.68   449.8 1228.93   464.8 1221.33   479.8 1218.46
   529.7 1218.65   574.6 1205.88   584.7 1205.02   589.6 1205.35   654.7 1212.33
   704.6 1230.31   754.6 1254.65   809.6 1257.10   924.5 1289.00   969.5 1288.28
  1014.5 1298.51  1069.4 1306.06  1149.4 1327.99  1199.4 1335.76  1279.3 1353.35
  1329.3 1366.02  1364.3 1380.35  1429.2 1400.71  1464.2 1406.77  1579.2 1445.58
#Mann= 3 , 0 , 0
       0     0.1       0   574.6   0.045       0   589.6     0.1       0
Bank Sta=   574.6,   589.6
Exp/Cntr=0.3,0.1

Type RM Length L Ch R = 1 ,2818,262.8,262.1,261.4
XS GIS Cut Line= 2
     1734847.187      198545.420     1735270.071      197691.413
#Sta/Elev= 30
       0 1404.10    69.8 1372.23   144.7 1342.23   164.6 1337.49   214.5 1316.76
   244.5 1307.72   309.3 1284.69   354.2 1256.96   359.2 1255.12   379.2 1252.53
   414.1 1237.11   494.0 1208.09   538.8 1200.99     554 1200.90   568.8 1199.52
     569 1199.53   583.8 1201.95   608.7 1211.27   618.7 1218.20   633.6 1231.52
   668.6 1255.61   688.5 1259.25   703.5 1263.86   708.5 1267.47   753.4 1314.43
   778.4 1334.52   838.2 1371.70   903.1 1407.86   928.0 1420.02   953.0 1429.24
#Mann= 3 , 0 , 0
       0     0.1       0     554   0.045       0     569     0.1       0
Bank Sta=     554,     569
Exp/Cntr=0.3,0.1

Type RM Length L Ch R = 1 ,2555.9,279,273.9,268.9
XS GIS Cut Line= 2
     1735119.041      198614.070     1735500.735      197773.793
#Sta/Elev= 30
       0 1402.21    39.9 1387.68    74.8 1376.58   124.7 1355.07   184.6 1327.29
   239.5 1295.11   319.3 1244.17   354.2 1226.03   384.1 1214.13   414.1 1209.78
   444.0 1208.13   454.0 1205.37   478.9 1194.40   488.9 1192.66   502.4 1192.10
   517.4 1192.42   538.8 1193.69   558.7 1199.52   568.7 1206.38   588.7 1223.51
   598.6 1230.45   678.5 1274.44   738.3 1315.74   773.2 1335.19   783.2 1339.57
   808.2 1348.07   853.1 1361.41   873.0 1369.44   888.0 1373.01   922.9 1383.74
#Mann= 3 , 0 , 0
       0     0.1       0   502.4   0.045       0   517.4     0.1       0
Bank Sta=   502.4,   517.4
Exp/Cntr=0.3,0.1

Type RM Length L Ch R = 1 ,2282,233.6,250.8,268.1
XS GIS Cut Line= 2
     1735465.037      198822.766     1735728.653      197548.621
#Sta/Elev= 30
       0 1401.73    69.8 1376.42   144.6 1353.52   219.4 1334.91   249.3 1325.32
   294.1 1303.04   358.9 1263.43   403.8 1229.72   438.7 1212.61   543.4 1198.99
   588.2 1184.12   599.4 1182.14   603.2 1182.09   614.4 1183.95   648.1 1198.35
   683.0 1202.16   712.9 1209.57   752.8 1225.62   787.7 1233.18   807.6 1240.16
   837.5 1247.27   857.4 1255.61   882.4 1262.46   902.3 1270.68   987.1 1297.69
  1056.9 1315.92  1091.8 1330.01  1131.6 1343.52  1221.4 1383.36  1301.1 1409.88
#Mann= 3 , 0 , 0
       0     0.1       0   599.4   0.045       0   614.4     0.1       0
Bank Sta=   599.4,   614.4
Exp/Cntr=0.3,0.1

Type RM Length L Ch R = 1 ,2031.2,397.6,383.8,369.9
XS GIS Cut Line= 4
     1735577.623      198767.846     1735606.723      198475.195
     1735965.915      198222.966     1736074.650      198004.458
#Sta/Elev= 30
       0 1416.77    54.8 1394.97    84.7 1380.90   124.6 1356.19   169.5 1333.68
   194.4 1318.26   264.2 1272.58   319.0 1234.17   344.0 1219.89   373.9 1206.74
   413.8 1192.18   428.8 1189.76   453.7 1188.94   493.6 1177.59   513.6 1176.68
   520.1 1176.91   528.5 1177.66   535.1 1179.41   558.4 1188.39   583.4 1200.56
   613.3 1211.87   643.2 1225.81   733.0 1275.13   817.7 1334.33   847.6 1352.57
   862.5 1363.46   887.4 1379.57   912.3 1398.57   952.2 1422.47   977.1 1435.35
#Mann= 3 , 0 , 0
       0     0.1       0   520.1   0.045       0   535.1     0.1       0
Bank Sta=   520.1,   535.1
Exp/Cntr=0.3,0.1

Type RM Length L Ch R = 1 ,1647.4,260.6,268.8,277.1
XS GIS Cut Line= 2
     1735926.366      199036.955     1736313.552      197955.030
#Sta/Elev= 30
       0 1376.72    55.0 1368.92    89.9 1360.91   154.9 1338.25   179.9 1326.41
   224.8 1300.75   304.8 1247.27   344.7 1222.66   379.7 1204.53   404.7 1185.75
   419.7 1181.72   444.7 1182.13   469.6 1179.64   479.6 1175.82   494.6 1166.48
   499.6 1166.05   505.4 1166.57   520.4 1169.05   534.6 1171.44   574.6 1174.28
   609.5 1180.45   634.5 1190.20   689.5 1208.45   774.4 1243.51   839.4 1266.33
   914.3 1304.67   984.2 1334.67  1044.2 1358.62  1114.2 1383.56  1149.1 1397.51
#Mann= 3 , 0 , 0
       0     0.1       0   505.4   0.045       0   520.4     0.1       0
Bank Sta=   505.4,   520.4
Exp/Cntr=0.3,0.1

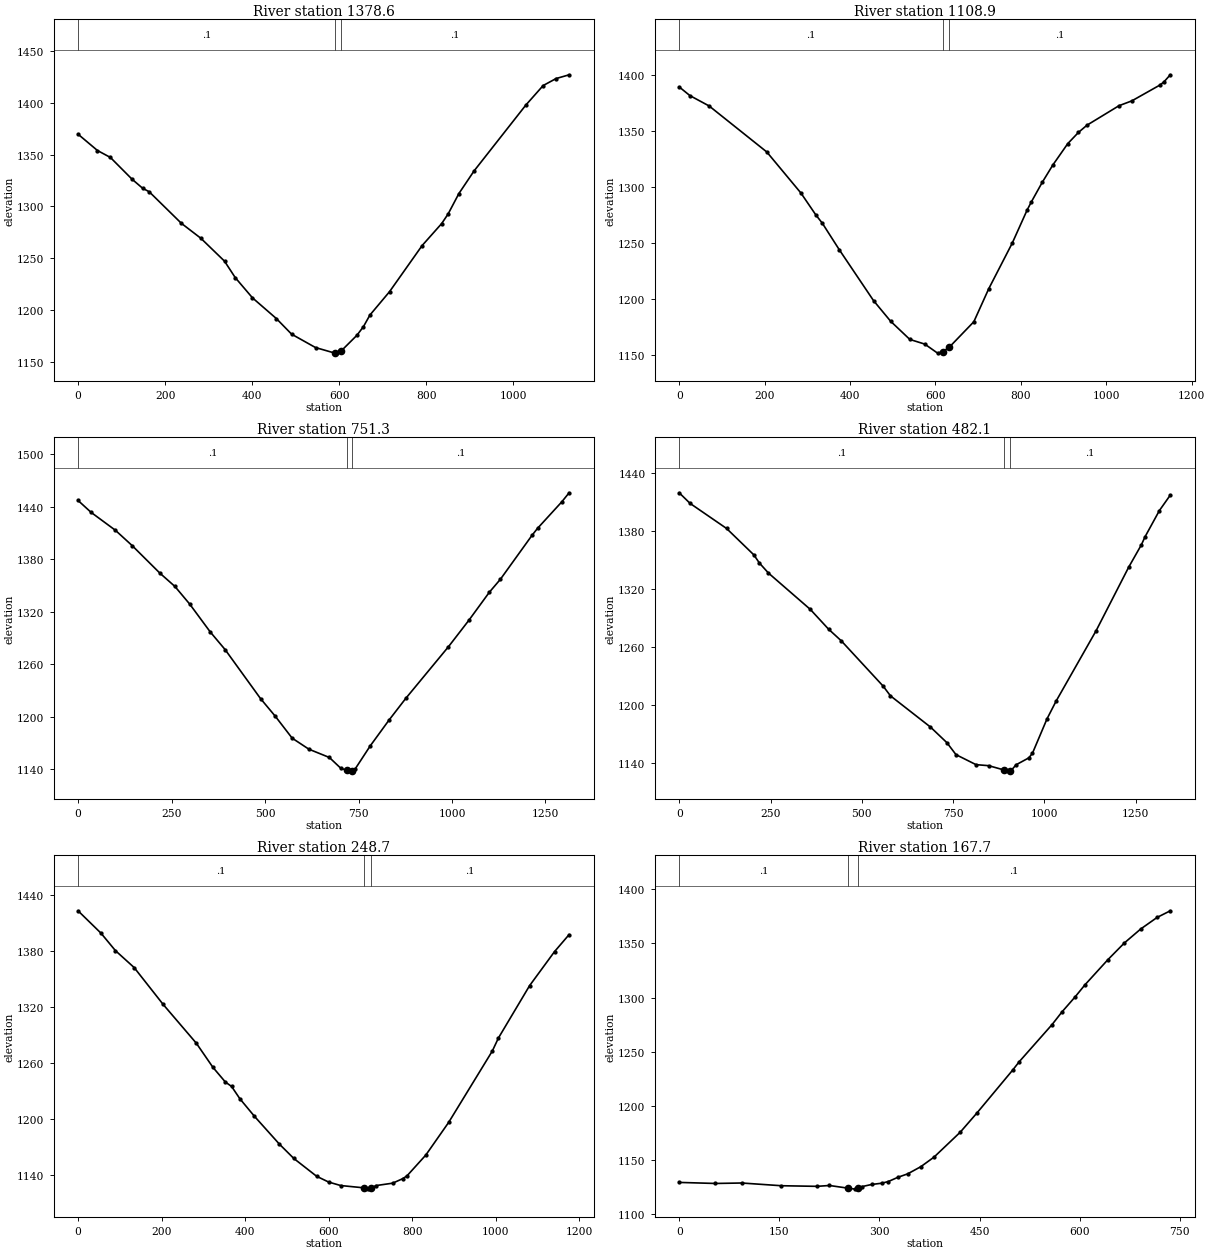
Type RM Length L Ch R = 1 ,1378.6,267.5,269.7,271.7
XS GIS Cut Line= 4
     1735909.890      199160.525     1736180.090      198851.197
     1736442.477      198555.977     1736656.802      198314.756
#Sta/Elev= 30
       0 1369.70    44.5 1354.00    74.2 1347.30   123.7 1326.42   148.4 1317.52
   163.3 1314.23   237.5 1283.66   282.1 1269.29   336.5 1247.18   361.2 1231.27
   400.8 1211.75   455.7 1191.76   490.7 1176.70   545.7 1163.77   590.2 1158.41
   590.7 1158.40   605.2 1160.74   640.7 1175.58   655.7 1183.90   670.7 1195.17
   715.7 1217.68   790.7 1262.27   835.5 1283.43   850.4 1292.73   875.2 1312.48
   909.9 1334.21  1029.1 1397.90  1068.8 1416.70  1098.6 1423.47  1128.4 1427.05
#Mann= 3 , 0 , 0
       0     0.1       0   590.2   0.045       0   605.2     0.1       0
Bank Sta=   590.2,   605.2
Exp/Cntr=0.3,0.1

Type RM Length L Ch R = 1 ,1108.9,373.5,357.6,341.8
XS GIS Cut Line= 2
     1736066.412      199297.825     1736895.705      198501.484
#Sta/Elev= 30
       0 1389.18    25.0 1381.47    70.0 1372.24   205.0 1331.25   284.9 1294.67
   319.9 1275.12   334.9 1267.83   374.9 1244.04   454.9 1198.80   494.9 1180.42
   539.9 1164.19   574.9 1160.03   604.9 1151.98   616.7 1153.28   631.7 1157.02
   689.8 1179.94   724.8 1209.43   779.8 1250.06   814.8 1279.66   824.8 1286.96
   849.8 1304.07   874.8 1319.63   909.8 1338.70   934.8 1348.68   954.8 1355.12
  1029.8 1372.49  1059.8 1376.78  1124.7 1390.70  1134.7 1393.57  1149.7 1399.99
#Mann= 3 , 0 , 0
       0     0.1       0   616.7   0.045       0   631.7     0.1       0
Bank Sta=   616.7,   631.7
Exp/Cntr=0.3,0.1

Type RM Length L Ch R = 1 ,751.3,266.4,269.2,271.9
XS GIS Cut Line= 3
     1736747.420      199720.709     1736848.183      198770.209
     1736980.831      198438.326
#Sta/Elev= 30
       0 1446.98    34.8 1433.41    99.6 1413.03   144.4 1395.54   219.0 1363.90
   258.9 1348.84   298.7 1328.55   353.5 1296.82   393.3 1276.63   487.9 1220.74
   527.7 1200.39   572.5 1175.53   617.3 1162.91   672.1 1153.44   701.9 1141.42
   718.6 1138.61   731.8 1137.86   733.6 1138.16   741.8 1140.83   781.6 1166.84
   831.4 1196.04   876.2 1220.84   990.6 1279.98  1045.2 1310.17  1099.8 1342.11
  1129.6 1357.06  1214.0 1407.16  1228.8 1415.16  1293.4 1445.30  1313.2 1455.74
#Mann= 3 , 0 , 0
       0     0.1       0   718.6   0.045       0   733.6     0.1       0
Bank Sta=   718.6,   733.6
Exp/Cntr=0.3,0.1

Type RM Length L Ch R = 1 ,482.1,244.2,233.4,222.6
XS GIS Cut Line= 3
     1736887.467      199918.421     1737143.825      198805.883
     1737140.099      198603.086
#Sta/Elev= 30
       0 1419.28    29.9 1408.29   129.6 1382.46   204.4 1355.14   219.4 1346.80
   244.3 1336.37   359.0 1298.81   408.8 1278.46   443.7 1266.38   558.4 1219.55
   578.3 1209.55   688.0 1177.25   732.9 1161.16   757.8 1148.78   812.6 1138.44
   847.5 1137.36   890.5 1132.80   905.5 1131.94   907.4 1131.74   922.3 1138.28
   957.2 1145.42   967.2 1150.21  1007.1 1185.77  1032.0 1204.11  1141.7 1276.94
  1230.7 1342.44  1265.4 1365.52  1275.3 1373.72  1314.8 1400.96  1344.5 1416.84
#Mann= 3 , 0 , 0
       0     0.1       0   890.5   0.045       0   905.5     0.1       0
Bank Sta=   890.5,   905.5
Exp/Cntr=0.3,0.1

Type RM Length L Ch R = 1 ,248.7,82.4,81,79.2
XS GIS Cut Line= 5
     1737250.969      199770.995     1737333.349      199210.811
     1737323.051      199134.609     1737298.337      199037.813
     1737166.529      198625.912
#Sta/Elev= 30
       0 1423.02    54.6 1399.22    89.4 1380.45   134.1 1362.39   203.6 1322.93
   283.1 1281.40   322.8 1255.61   352.6 1239.88   367.5 1235.16   387.4 1221.96
   422.2 1203.24   481.8 1173.52   516.5 1158.12   571.0 1139.10   599.8 1132.90
   628.7 1129.17   685.5 1126.66   693.0 1125.33   700.5 1126.05   713.0 1129.11
   753.0 1131.69   777.8 1136.63   787.7 1139.66   832.5 1161.79   887.2 1196.72
   991.6 1272.97  1006.5 1287.12  1081.0 1343.02  1140.7 1379.42  1175.5 1397.56
#Mann= 3 , 0 , 0
       0     0.1       0   685.5   0.045       0   700.5     0.1       0
Bank Sta=   685.5,   700.5
Exp/Cntr=0.3,0.1

Type RM Length L Ch R = 1 ,167.7,108.7,112.6,116.9
XS GIS Cut Line= 5
     1737467.382      199294.460     1737384.948      199120.691
     1737391.911      199074.346     1737305.796      198823.188
     1737204.287      198615.529
#Sta/Elev= 30
       0 1129.46    54.2 1128.50    93.7 1128.92   152.9 1126.41   206.4 1125.84
   225.1 1126.62   253.3 1124.12   263.8 1123.27   268.3 1124.29   273.6 1125.57
   288.4 1127.57   303.1 1128.70   313.0 1130.19   327.7 1134.20   342.4 1137.38
   362.1 1144.01   381.8 1152.80   421.1 1175.80   445.7 1193.22   499.8 1233.21
   509.6 1240.91   558.8 1275.17   573.6 1286.82   593.2 1300.62   608.0 1311.79
   642.4 1335.02   667.0 1350.39   691.6 1363.33   716.2 1374.01   735.8 1380.07
#Mann= 3 , 0 , 0
       0     0.1       0   253.3   0.045       0   268.3     0.1       0
Bank Sta=   253.3,   268.3
Exp/Cntr=0.3,0.1

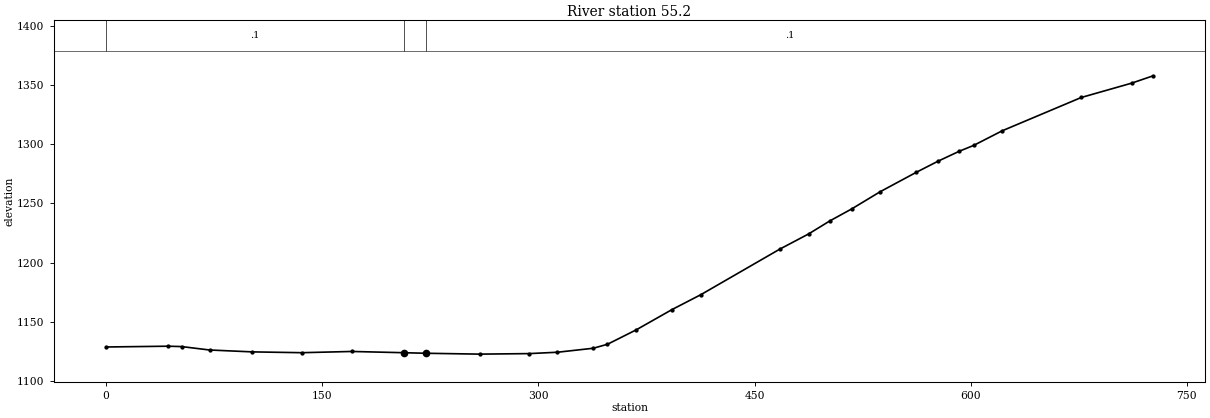
Type RM Length L Ch R = 1 ,55.2,65.8,55.2,49.3
XS GIS Cut Line= 5
     1737458.725      199221.928     1737467.393      199160.517
     1737494.005      199045.122     1737473.395      198903.945
     1737240.671      198574.425
#Sta/Elev= 30
       0 1128.80    42.9 1129.46    52.5 1129.15    71.9 1126.26   101.5 1124.67
   136.0 1123.98   170.6 1125.02   206.9 1123.96   221.9 1123.50   259.2 1122.77
   293.6 1123.21   313.3 1124.37   338.1 1127.73   348.0 1131.10   367.9 1143.26
   392.8 1160.43   412.8 1173.00   467.6 1211.49   487.5 1224.26   502.4 1235.38
   517.4 1245.39   537.3 1260.01   562.2 1276.30   577.1 1285.58   592.1 1294.14
   602.0 1299.02   621.9 1311.42   676.7 1339.52   711.6 1351.61   726.5 1357.81
#Mann= 3 , 0 , 0
       0     0.1       0   206.9   0.045       0   221.9     0.1       0
Bank Sta=   206.9,   221.9
Exp/Cntr=0.3,0.1